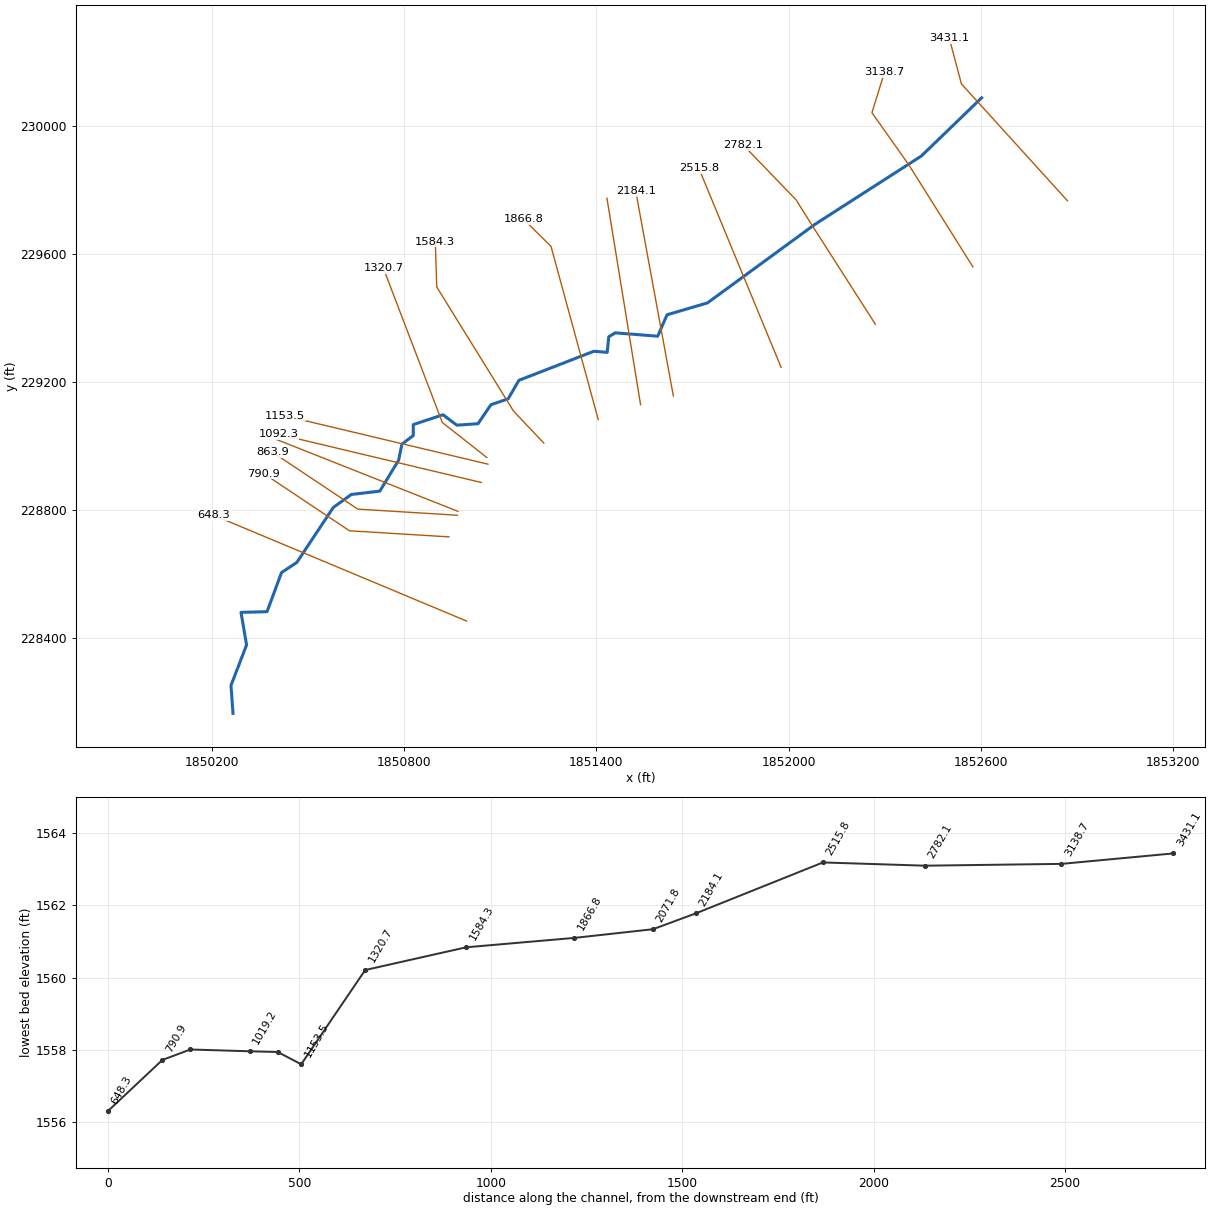
--- T1GLADECK.prj (project) ---

Proj Title=T1GLADECK
Current Plan=p01
Default Exp/Contr=0,0
English Units
Geom File=g01
Flow File=f01
Plan File=p01
BEGIN DESCRIPTION:
END DESCRIPTION:
DSS Export Rating Curves= 0
DSS Export Rating Curve Sorted= 0
DSS Export Volume Flow Curves= 0
DXF OffsetX= 0
DXF OffsetY= 0
DXF ScaleX= 0
DXF ScaleY= 0

--- T1GLADECK.p01 (plan) ---

Plan Title=Floodplain
Program Version=4.00
Geom File=g01
Flow File=f01
K Sum by GR=0
Std Step Tol=0.01
Critical Tol=0.01
Num of Std Step Trials=20
Max Error Tol=0.3
Flow Tol Ratio=0.001
Split Flow NTrial=30
Split Flow Tol=0.02
Split Flow Ratio=0.02
Log Output Level=0
Friction Slope Method=1
Unsteady Friction Slope Method=2
Unsteady Bridges Friction Slope Method=1
Global Log Level=0
CheckData=False
Run HTab=0
Run UNet=0
Run PostProcess=0
UNET Theta=0
UNET Theta Warmup=0
UNET ZTol=0
UNET ZSATol=0
UNET MxIter=0
UNET MaxInSteps=0
UNET DtIC=0
UNET DtMin=0
UNET MaxCRTS=0
UNET WFStab=0
UNET SFStab=0
UNET WFX=0
UNET SFX=0
UNET DSS MLevel=0
UNET DZMax Abort=0
UNET Convert EG Bridges=0
UNET Use Existing IB Tables=0
UNET Froude Limit=0
UNET Froude Power=0
Write IC File=0
Echo Input=False
Echo Output=False
Write Detailed=0

--- T1GLADECK.f01 (steady flow) ---

Flow Title=NFF Regression Equation
Program Version=4.00
Number of Profiles=1
Profile Names=P100yr
River Rch & RM=T1GLADECK,Main      ,3431.1
519.1538
River Rch & RM=T1GLADECK,Main      ,2071.8
595.7747
River Rch & RM=T1GLADECK,Main      ,1153.5
606.4321
River Rch & RM=T1GLADECK,Main      ,863.9
732.9264
Boundary for River Rch & Prof#=T1GLADECK,Main      ,1
Up Type=0
Dn Type=3
Dn Slope=0.000945

--- T1GLADECK.g01 (geometry) ---

Geom Title=USGS 10m DEM
Program Version=4.10

River Reach=T1GLADECK       ,Main
Reach XY= 30
     1852602.508      230089.598     1852414.461      229907.643
     1852081.618      229693.457      1851746.78      229448.101
     1851620.525      229410.915     1851591.285      229343.866
     1851458.732      229354.472     1851438.594      229341.972
     1851433.732      229293.361     1851392.066      229296.833
     1851158.038      229205.861     1851124.705      229148.222
     1851070.754      229129.573     1851030.515      229070.358
     1850964.429      229065.557     1850921.232      229098.223
     1850828.437      229067.412     1850828.299      229033.234
     1850792.772      229005.916      1850782.83      228956.376
      1850724.01      228859.334     1850635.121      228848.917
     1850578.923      228808.473     1850464.982      228636.417
     1850417.066      228604.473     1850371.927       228482.25
     1850290.677      228480.167     1850308.058      228378.143
     1850259.427      228251.695     1850265.677      228164.195

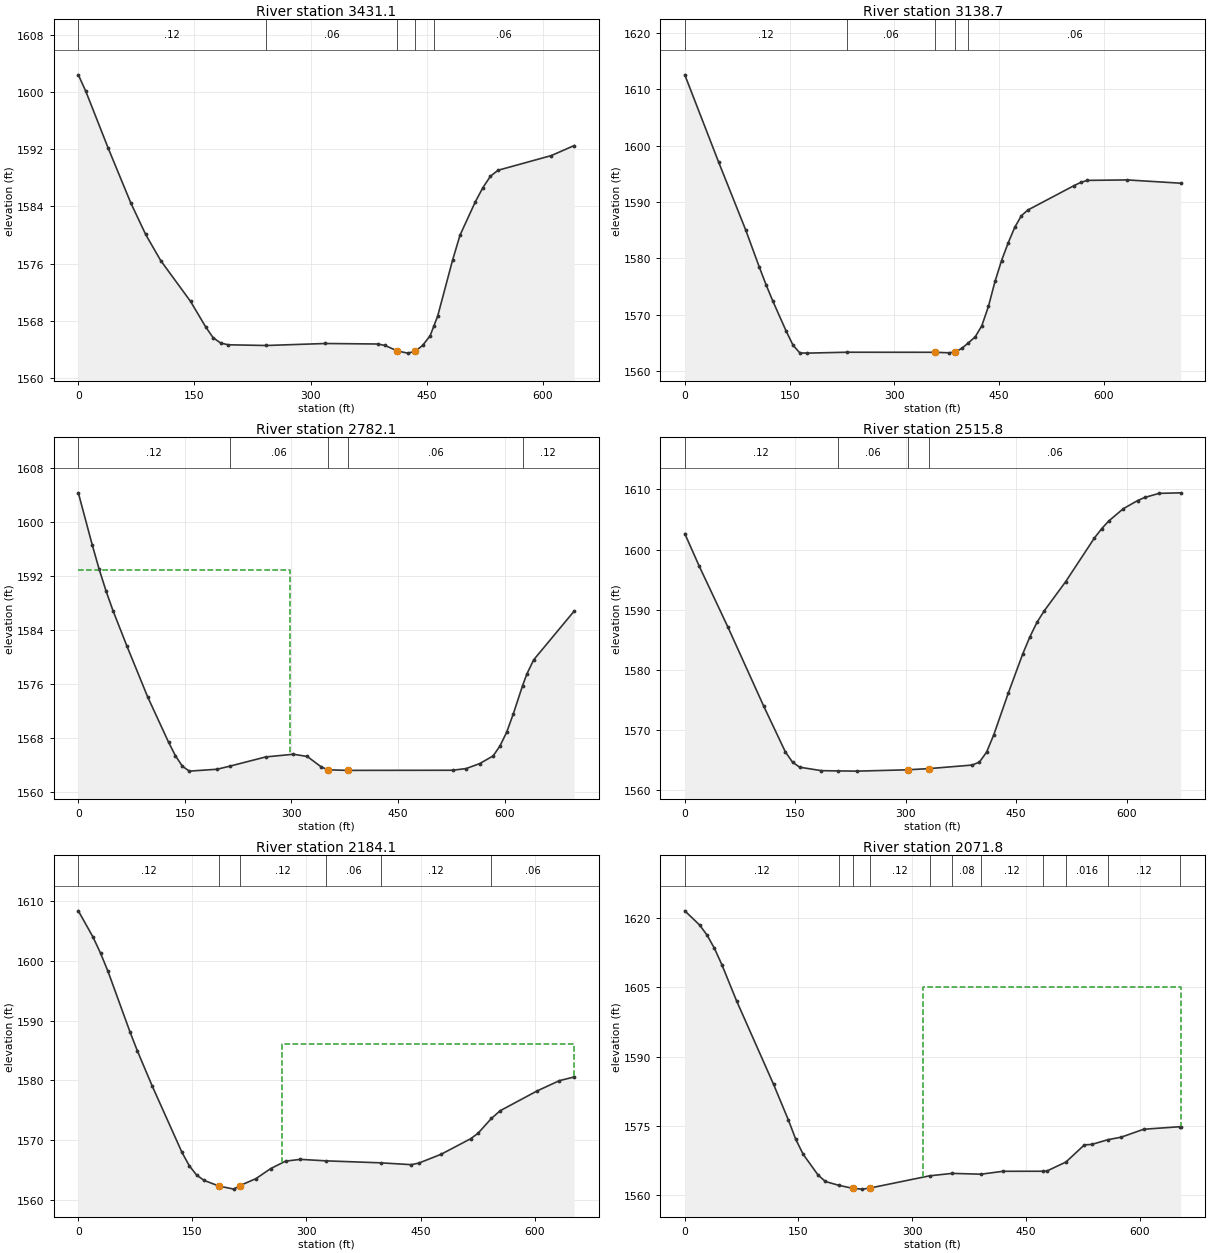
Type RM Length L Ch R = 1 ,3431.1  ,298.9,292.4,287.8
XS GIS Cut Line= 3
     1852870.387      229767.553     1852539.345      230133.118
     1852501.628      230275.614
#Sta/Elev= 30
       0 1602.46     9.7 1600.14    38.7 1592.15    67.7 1584.52      87 1580.08
   106.4 1576.42     145 1570.69   164.4 1567.14   174.1 1565.61   183.7 1564.87
   193.4 1564.61  242.79 1564.51   319.1 1564.79   386.8 1564.72   396.5 1564.51
     412 1563.75   425.5 1563.44   435.2 1563.69   444.8 1564.52   454.5 1565.87
  459.531567.291   464.2 1568.61   483.5 1576.47   493.2    1580   512.8 1584.63
   522.7 1586.65   532.5 1588.25   542.3 1589.08   611.1 1591.14   640.6 1592.54
#Mann= 5 ,-1 , 0
       0     .12       0  242.79     .06       0     412    .045       0
   435.2     .12       0  459.53     .06       0
Bank Sta=412,435.2
XS Rating Curve= 0 ,0
Exp/Cntr=0.3,0.1

Type RM Length L Ch R = 1 ,3138.7  ,356.3,356.6,354.5
XS GIS Cut Line= 4
     1852575.174       229560.83      1852374.48      229881.019
     1852260.068      230043.034     1852299.606      230170.489
#Sta/Elev= 30
       0 1612.56    48.4 1597.07    87.2 1585.01   106.6 1578.44   116.3  1575.3
     126 1572.39   145.3 1567.01     155 1564.54   164.7 1563.19   174.4 1563.15
  231.77 1563.31   358.5  1563.3   377.9 1563.21   387.3 1563.34   396.8 1564.03
  405.42 1564.92   415.7 1566.04   425.1    1568   434.6 1571.44     444 1575.87
   453.4 1579.59   462.9 1582.73   472.3 1585.49   481.8 1587.55   491.2 1588.57
   557.3  1592.9   566.8 1593.46   576.2 1593.82   633.4  1593.9   709.7 1593.32
#Mann= 5 ,-1 , 0
       0     .12       0  231.77     .06       0   358.5    .045       0
   387.3     .12       0  405.42     .06       0
Bank Sta=358.5,387.3
XS Rating Curve= 0 ,0
Exp/Cntr=0.3,0.1

Type RM Length L Ch R = 1 ,2782.1  ,273.3,266.3,259.8
XS GIS Cut Line= 4
     1852270.709      229381.455     1852070.961       229694.28
     1852023.677      229769.968     1851859.044      229941.237
#Sta/Elev= 30
       0 1604.31    19.5 1596.63    29.3    1593    39.1 1589.75    48.8 1586.86
    68.4 1581.62    97.7 1574.07     127 1567.39   136.7 1565.38   146.5 1563.82
   156.3  1563.1   195.4 1563.38  213.611563.846   263.7  1565.2   302.8  1565.6
   322.3 1565.27   341.9 1563.73   351.6 1563.29   380.1 1563.21   526.9 1563.23
   545.9 1563.48   564.9 1564.21   583.9 1565.35   593.4  1566.8   602.9 1568.84
   612.4  1571.6  625.281575.729   631.4 1577.48     641 1579.58     698  1586.8
#Mann= 5 ,-1 , 0
       0     .12       0  213.61     .06       0   351.6    .045       0
   380.1     .06       0  625.28     .12       0
#XS Ineff= 2 , 0
          298.36 1592.91
Permanent Ineff=
       F       F
Bank Sta=351.6,380.1
XS Rating Curve= 0 ,0
Exp/Cntr=0.3,0.1

Type RM Length L Ch R = 1 ,2515.8  ,346.2,331.7,297.5
XS GIS Cut Line= 2
     1851976.661      229246.408     1851719.925      229868.845
#Sta/Elev= 30
       0 1602.65    19.5 1597.27    58.6 1587.11   107.3 1573.95   136.6 1566.38
   146.4 1564.66   156.1 1563.84   185.4 1563.27  207.681563.226   234.2 1563.19
   302.5 1563.41   331.8 1563.61   390.3  1564.2   400.1  1564.7   409.8 1566.34
   419.6 1569.24   439.1 1576.09   458.6 1582.57   468.4 1585.45   478.2  1587.9
   487.9 1589.79   517.2 1594.67   556.2 1601.92     566 1603.46   575.7 1604.75
   595.2 1606.77   614.8 1608.14   624.5 1608.66     644 1609.34   673.3 1609.43
#Mann= 4 ,-1 , 0
       0     .12       0  207.68     .06       0   302.5    .045       0
   331.8     .06       0
Bank Sta=302.5,331.8
XS Rating Curve= 0 ,0
Exp/Cntr=0.3,0.1

Type RM Length L Ch R = 1 ,2184.1  ,107.4,112.3,130.8
XS GIS Cut Line= 2
     1851640.235      229157.008      1851522.66      229798.325
#Sta/Elev= 30
       0 1608.43    19.5 1603.98    29.2 1601.33    38.9 1598.32    68.1 1588.08
    77.8  1584.9    97.3 1579.02   136.2 1567.96     146 1565.68   155.7 1564.12
   165.4 1563.24   184.9  1562.3   204.4 1561.78   212.6 1562.38   233.6 1563.54
     253 1565.23   272.5 1566.47   291.9 1566.77  325.81 1566.52  397.381566.188
   437.9 1565.88   447.6 1566.14   476.8 1567.61   515.8 1570.22   525.5 1571.13
   543.21573.636   554.7 1574.92   603.4 1578.25   632.5 1579.96     652 1580.58
#Mann= 6 ,-1 , 0
       0     .12       0   184.9    .045       0   212.6     .12       0
  325.81     .06       0  397.38     .12       0   543.2     .06       0
#XS Ineff= 2 , 0
                          268.35         1586.08
Permanent Ineff=
       F       F
Bank Sta=184.9,212.6
XS Rating Curve= 0 ,0
Exp/Cntr=0.3,0.1

Type RM Length L Ch R = 1 ,2071.8  ,200.6,205.1,188.6
XS GIS Cut Line= 2
     1851537.899      229129.814      1851432.97      229775.529
#Sta/Elev= 30
       0 1621.53    19.5 1618.47    29.3  1616.3    39.1 1613.42    48.8 1609.92
    68.4 1602.03   117.2 1583.97   136.7 1576.28   146.5 1572.08   156.2 1568.87
   175.8  1564.4   185.5 1562.99  202.861562.179   222.2 1561.49   234.3 1561.34
   244.1 1561.57  322.891564.216   352.91564.746  390.981564.571   419.8  1565.2
  472.931565.208   478.4 1565.31  502.941567.205   527.2 1570.91     537 1571.01
  558.111572.025   576.1 1572.59   605.4 1574.29  652.981574.835   654.2 1574.86
#Mann= 11 ,-1 , 0
       0     .12       0  202.86     .06       0   222.2    .045       0
   244.1     .12       0  322.89     .06       0   352.9     .08       0
  390.98     .12       0  472.93     .06       0  502.94    .016       0
  558.11     .12       0  652.98     .06       0
#XS Ineff= 2 , 0
                          314.25            1605
Permanent Ineff=
       F       F
Bank Sta=222.2,244.1
XS Rating Curve= 0 ,0
Exp/Cntr=0.3,0.1

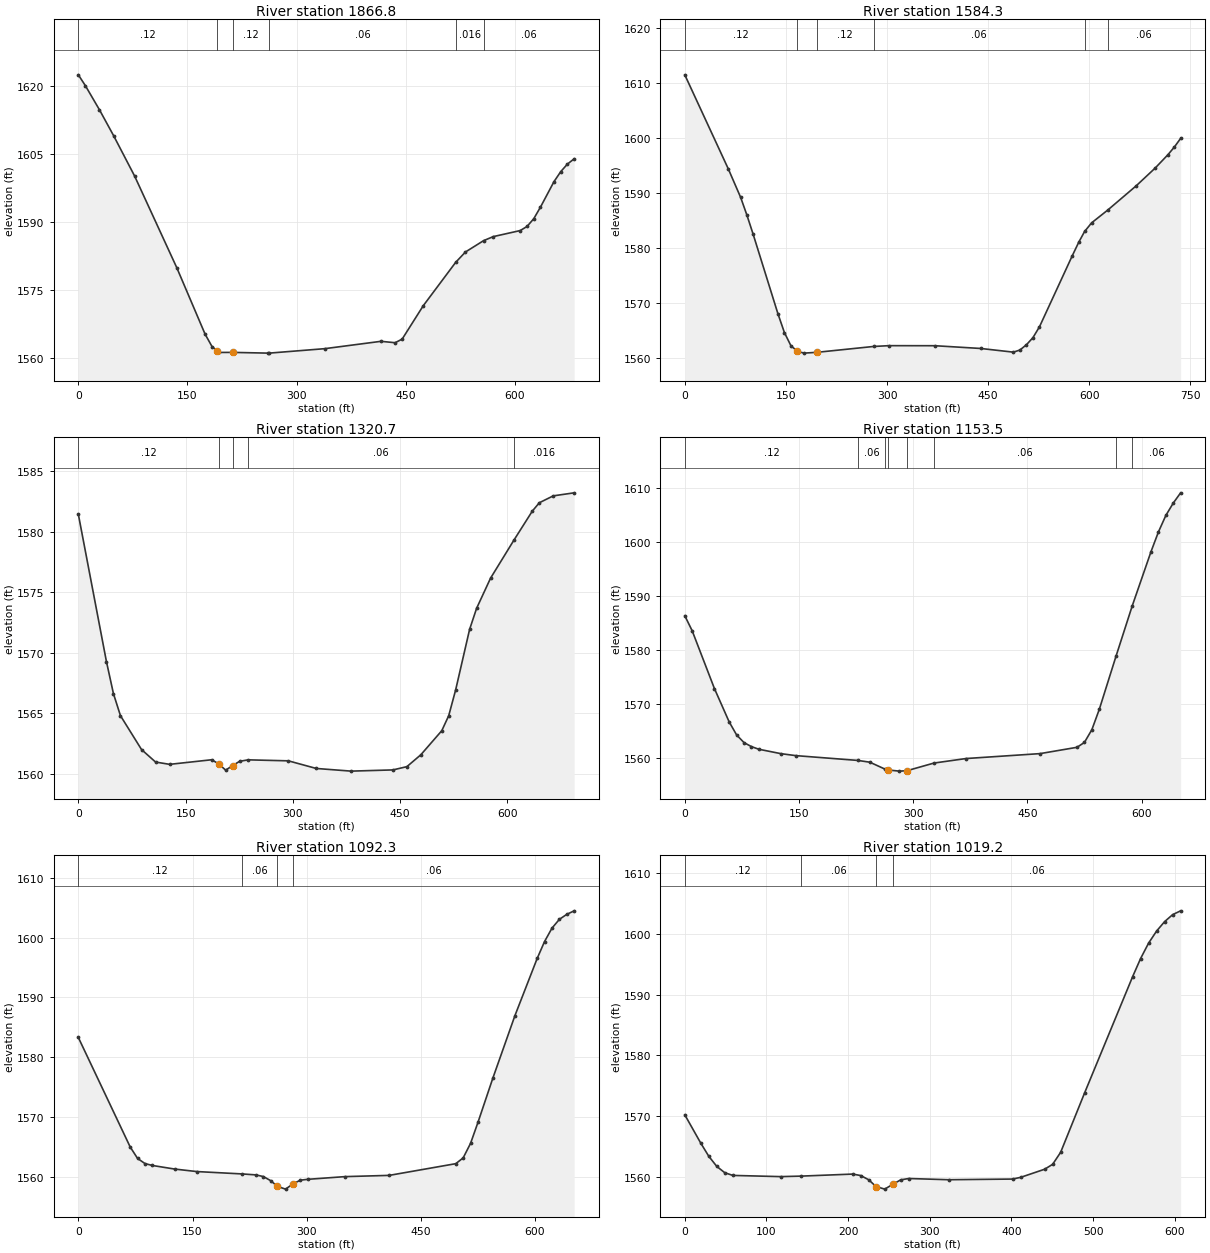
Type RM Length L Ch R = 1 ,1866.8  ,271.2,282.5,293
XS GIS Cut Line= 3
     1851405.813      229083.211     1851258.376      229624.662
     1851173.013      229709.456
#Sta/Elev= 30
       0 1622.38     9.7 1619.99      29 1614.69    48.4 1609.01    77.4 1600.08
   135.4 1579.88   174.2 1565.29   183.8 1562.53   190.8 1561.61   193.5 1561.25
   212.9 1561.26   261.2  1561.1  262.381561.102   338.6 1562.08     416  1563.7
   435.4 1563.39   445.1 1564.19   474.1 1571.54  518.671581.094   532.1 1583.37
   557.11585.877   570.4 1586.76   607.4 1588.09   616.7 1588.99     626  1590.7
   635.2 1593.25   653.7 1598.84     663 1601.05   672.2 1602.72   681.5 1603.89
#Mann= 6 ,-1 , 0
       0     .12       0   190.8    .045       0   212.9     .12       0
  262.38     .06       0  518.67    .016       0   557.1     .06       0
Bank Sta=190.8,212.9
XS Rating Curve= 0 ,0
Exp/Cntr=0.3,0.1

Type RM Length L Ch R = 1 ,1584.3  ,204,263.6,255.5
XS GIS Cut Line= 4
     1851235.982      229009.469     1851141.188      229109.905
     1850901.605      229497.926     1850897.185       229639.35
#Sta/Elev= 30
       0 1611.54    64.4 1594.44    82.9  1589.2    92.1    1586   101.3 1582.54
   138.1 1568.04   147.8 1564.58   157.5 1562.17   167.2 1561.18   176.9 1560.84
   196.3 1560.99  280.141562.054     303  1562.2     371 1562.19   438.9 1561.69
   487.4 1561.02   497.1  1561.4   506.8 1562.36   516.5 1563.66   526.2 1565.64
   574.7 1578.54   584.4 1581.03  593.131583.001   603.6 1584.58  627.231586.879
   669.6 1591.31   697.9 1594.56   716.8 1596.99   726.2 1598.37   735.6 1599.96
#Mann= 6 ,-1 , 0
       0     .12       0   167.2    .045       0   196.3     .12       0
  280.14     .06       0  593.13    .016       0  627.23     .06       0
Bank Sta=167.2,196.3
XS Rating Curve= 0 ,0
Exp/Cntr=0.3,0.1

Type RM Length L Ch R = 1 ,1320.7  ,180.7,167.1,200.1
XS GIS Cut Line= 3
     1851058.028      228964.506      1850919.14      229073.881
     1850735.112       229556.52
#Sta/Elev= 30
       0 1581.43    39.3 1569.26    49.1 1566.61    58.9 1564.79    88.4 1561.99
     108 1560.96   127.7 1560.77   186.5 1561.15   196.3 1560.81     206 1560.29
   215.8 1560.67   225.5 1561.02  237.441561.142   293.7 1561.06   332.7 1560.43
   381.4 1560.21   439.9 1560.31   459.4 1560.58   478.9 1561.56   508.2 1563.55
   517.9 1564.79   527.6 1566.92   547.1 1571.92   556.9 1573.66   576.4 1576.15
  608.911579.277   634.8 1581.69   644.6 1582.38   664.1 1582.95   693.3  1583.2
#Mann= 5 ,-1 , 0
       0     .12       0   196.3    .045       0   215.8     .12       0
  237.44     .06       0  608.91    .016       0
Bank Sta=196.3,215.8
XS Rating Curve= 0 ,0
Exp/Cntr=0.3,0.1

Type RM Length L Ch R = 1 ,1153.5  ,70.1,61.2,61.1
XS GIS Cut Line= 2
     1851061.501      228943.673      1850427.82      229094.714
#Sta/Elev= 30
       0 1586.36     9.7 1583.57    38.9 1572.89    58.3 1566.71    68.1 1564.29
    77.8 1562.88    87.5 1562.14    97.2 1561.65   126.4 1560.83   145.8 1560.47
  227.651559.576   243.1 1559.25  263.66 1557.93   267.1 1557.81     282  1557.6
   291.7 1557.67  327.361559.094   369.5 1559.93   466.7 1560.84   515.3 1562.01
     525 1562.91   534.8 1565.27   544.5 1569.01  566.541578.872  587.83 1588.18
   612.5 1598.22   622.3 1601.88     632 1604.92   641.7  1607.2   651.4  1609.1
#Mann= 8 ,-1 , 0
       0     .12       0  227.65     .06       0  263.66     .12       0
   267.1    .045       0   291.7     .12       0  327.36     .06       0
  566.54     .12       0  587.83     .06       0
Bank Sta=267.1,291.7
XS Rating Curve= 0 ,0
Exp/Cntr=0.3,0.1

Type RM Length L Ch R = 1 ,1092.3  ,78.4,73,67.6
XS GIS Cut Line= 2
     1851040.667      228886.381     1850406.987      229037.423
#Sta/Elev= 30
       0 1583.31    68.1    1565    77.8 1563.08    87.5 1562.22    97.2  1561.9
   126.4  1561.3   155.6 1560.88  214.981560.484   233.4 1560.32   243.1 1560.04
   252.8 1559.35   261.4 1558.41   272.2 1557.94     282 1558.81   291.7 1559.44
   301.4 1559.58     350 1560.03   408.4 1560.24   495.9  1562.2   505.6 1563.17
   515.3  1565.6     525  1569.1   544.5 1576.48   573.6 1586.97   602.8 1596.53
   612.5 1599.36   622.3 1601.61     632 1603.08   641.7 1603.91   651.4  1604.5
#Mann= 4 ,-1 , 0
       0     .12       0  214.98     .06       0   261.4    .045       0
     282     .06       0
Bank Sta=261.4,282
XS Rating Curve= 0 ,0
Exp/Cntr=0.3,0.1

Type RM Length L Ch R = 1 ,1019.2  ,162.9,155.3,145.5
XS GIS Cut Line= 2
     1850967.751      228796.103     1850403.515      229020.062
#Sta/Elev= 30
       0 1570.21    19.6 1565.53    29.4 1563.37    39.2  1561.7      49 1560.66
    58.8 1560.22   117.5 1560.02   142.61560.106   205.6 1560.44   215.4  1560.2
   225.2  1559.5   234.1 1558.39   244.8 1557.96   254.6 1558.75   264.4 1559.49
   274.2 1559.71   323.1 1559.51   401.4 1559.62   411.2  1559.9   440.6 1561.24
   450.4 1562.05   460.2 1564.03   489.6 1573.84   548.3 1592.97   558.1 1595.97
   567.9 1598.51   577.7  1600.5   587.5 1602.05   597.3  1603.2   607.1 1603.83
#Mann= 4 ,-1 , 0
       0     .12       0   142.6     .06       0   234.1    .045       0
   254.6     .06       0
Bank Sta=234.1,254.6
XS Rating Curve= 0 ,0
Exp/Cntr=0.3,0.1

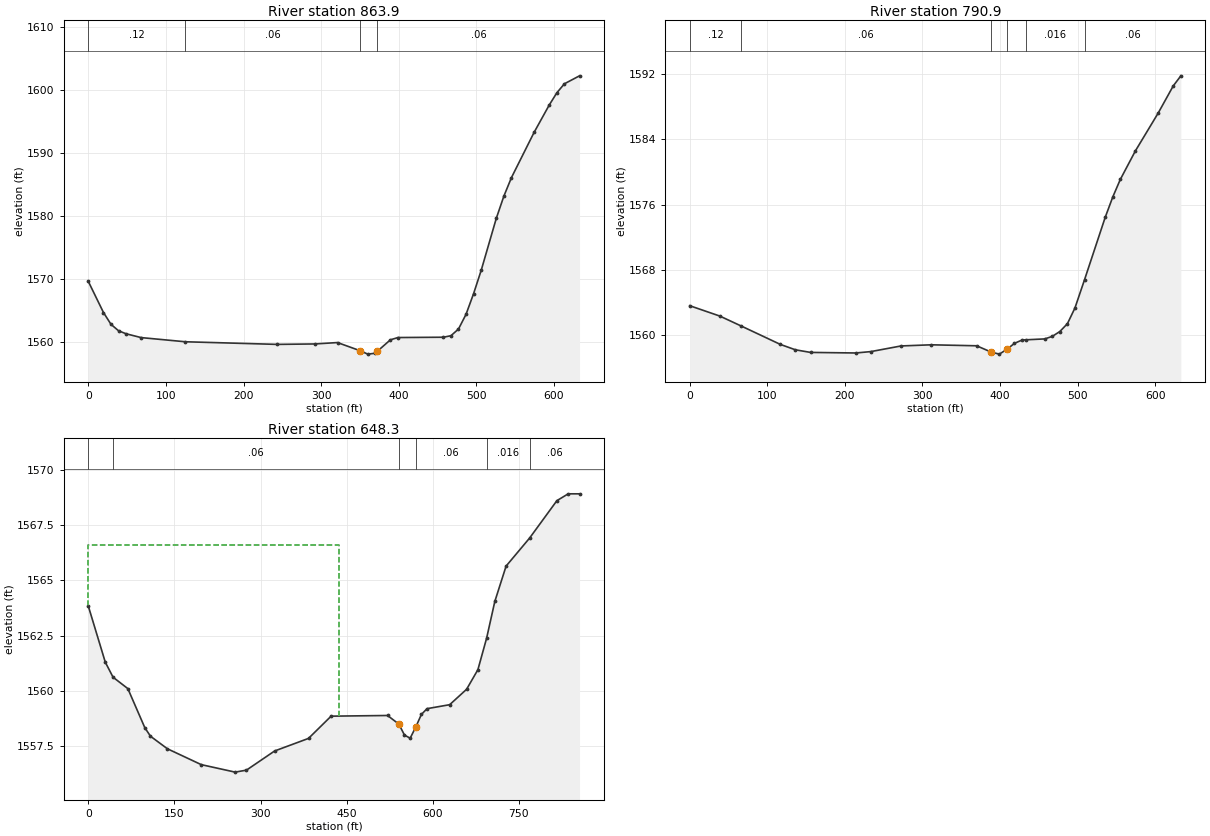
Type RM Length L Ch R = 1 ,863.9   ,73,73,72.3
XS GIS Cut Line= 3
     1850966.015      228783.951     1850655.251      228803.048
      1850387.89      228981.867
#Sta/Elev= 30
       0 1569.57    19.5 1564.63    29.2 1562.75    38.9 1561.73    48.6 1561.25
    68.1 1560.64  124.871559.978   243.2 1559.56   291.9 1559.63   321.1 1559.85
   350.3 1558.55   360.1 1558.01   369.8 1558.15   372.5 1558.47   389.3 1560.29
   399.1 1560.65   457.6  1560.7   467.3 1560.94     477    1562   486.8 1564.36
   496.5 1567.64   506.3 1571.35   525.8 1579.64   535.5 1583.15   545.3 1586.11
   574.5 1593.31     594 1597.66   603.8  1599.6   613.5 1601.03     633  1602.3
#Mann= 4 ,-1 , 0
       0     .12       0  124.87     .06       0   350.3    .045       0
   372.5     .06       0
Bank Sta=350.3,372.5
XS Rating Curve= 0 ,0
Exp/Cntr=0.3,0.1

Type RM Length L Ch R = 1 ,790.9   ,134.4,142.6,148.9
XS GIS Cut Line= 3
     1850939.973      228716.242     1850629.209      228735.339
     1850361.848      228914.159
#Sta/Elev= 30
       0 1563.64    38.9 1562.37   66.271561.163   116.8 1558.91   136.2 1558.25
   155.7 1557.93     214 1557.86   233.5 1558.03   272.4 1558.72   311.4 1558.86
   369.8 1558.74   388.8 1557.96   399.1 1557.72   408.8 1558.31   418.6 1559.04
   428.3 1559.44  433.24 1559.47   457.6 1559.58   467.3 1559.89     477 1560.48
   486.8 1561.44   496.5 1563.36  508.831566.807   535.5 1574.44   545.3 1576.94
     555 1579.08   574.5 1582.58   603.8 1587.19   623.2 1590.51     633 1591.74
#Mann= 6 ,-1 , 0
       0     .12       0   66.27     .06       0   388.8    .045       0
   408.8     .06       0  433.24    .016       0  508.83     .06       0
Bank Sta=388.8,408.8
XS Rating Curve= 0 ,0
Exp/Cntr=0.3,0.1

Type RM Length L Ch R = 1 ,648.3   ,584.5,648.3,666.1
XS GIS Cut Line= 2
      1850994.66      228453.048     1850205.598      228783.777
#Sta/Elev= 30
       0 1563.83    29.5 1561.29   43.051560.607    68.8 1560.09    98.3 1558.32
   108.2 1557.93   137.7 1557.36   196.7 1556.64   255.7  1556.3   275.4 1556.39
   324.5 1557.26   383.5 1557.83   422.9 1558.84   521.2 1558.87   540.9 1558.48
   550.7 1557.98   560.6 1557.84   570.4 1558.35   580.2 1558.92     590 1559.18
   629.4 1559.36   658.9 1560.06   678.6 1560.95  693.761562.379   708.1 1564.05
   727.7 1565.65  768.811566.928   816.2 1568.62   835.9 1568.93   855.6 1568.93
#Mann= 6 ,-1 , 0
       0     .12       0   43.05     .06       0   540.9    .045       0
   570.4     .06       0  693.76    .016       0  768.81     .06       0
#XS Ineff= 2 , 0
          436.32 1566.61
Permanent Ineff=
       F       F
Bank Sta=540.9,570.4
XS Rating Curve= 0 ,0
Exp/Cntr=0.3,0.1

Chan Stop Cuts=-1
Use User Specified Reach Order=0
Composite Channel Slope=5